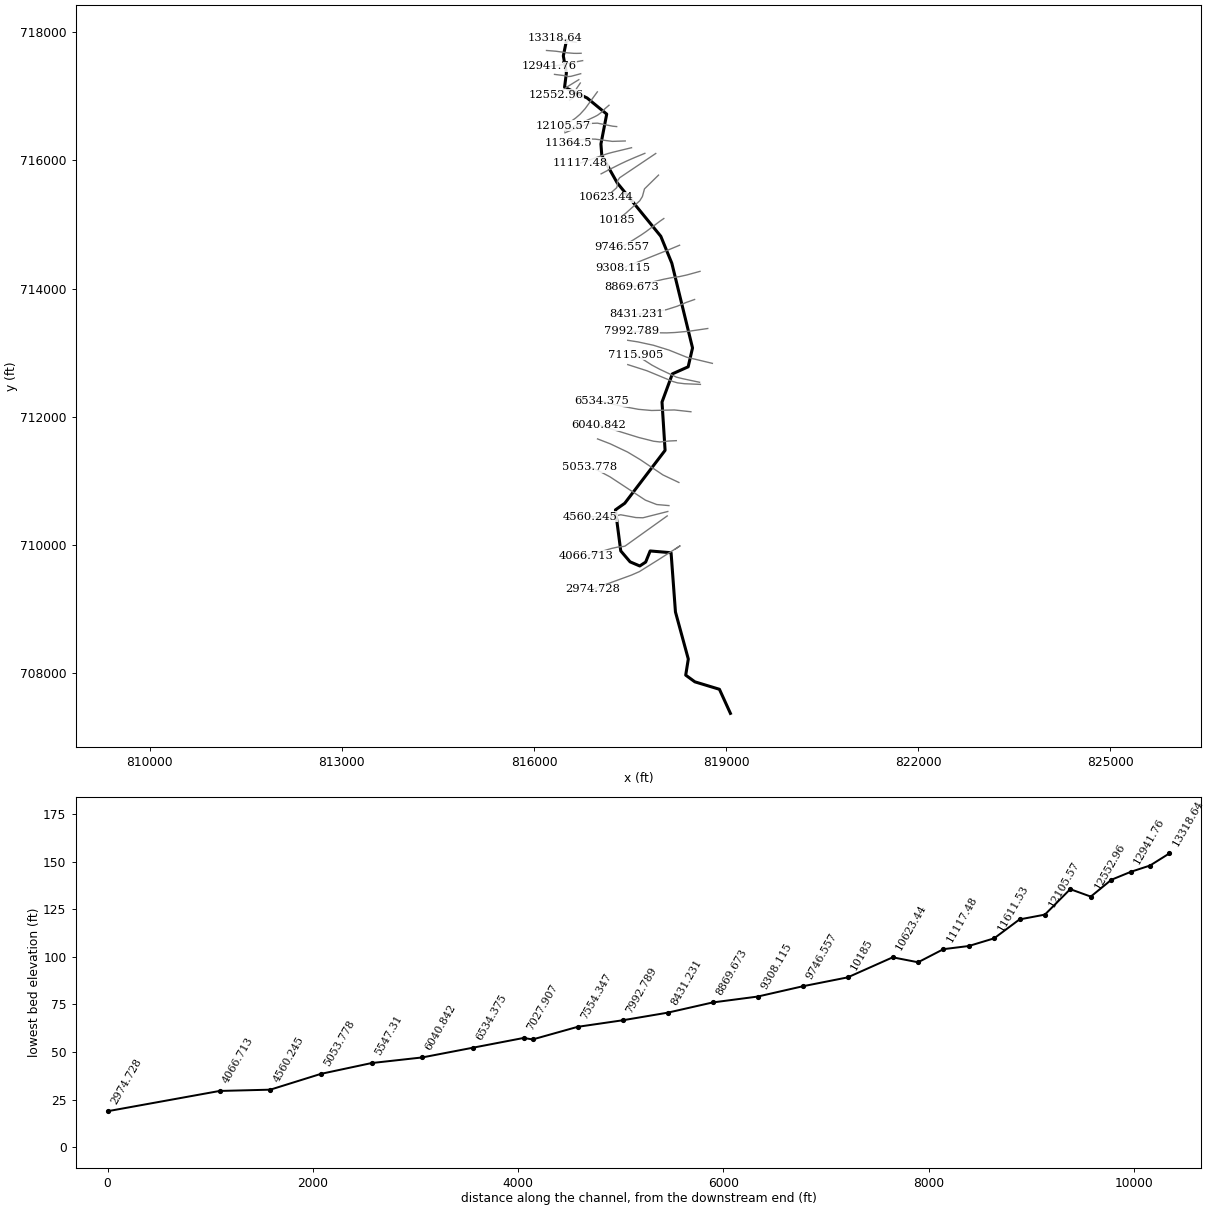
--- 7002_ras.prj (project) ---

Proj Title=7002
Current Plan=p01
Default Exp/Contr=0.3,0.1
English Units
Geom File=g01
Flow File=f01
Plan File=p01
Y Axis Title=Elevation
X Axis Title(PF)=Main Channel Distance
X Axis Title(XS)=Station
BEGIN DESCRIPTION:
RFD model 7002 exported to HEC-RAS
END DESCRIPTION:

--- 7002_ras.p01 (plan) ---

Plan Title=Plan 01
Program Version=4.10
Short Identifier=Plan 01
Geom File=g01
Flow File=f01
Subcritical Flow
Calc Critical at every XS
Secant Critical Depth

--- 7002_ras.f01 (steady flow) ---

Flow Title=Flow 01
Program Version=5.01
Number of Profiles= 6
Profile Names=10yr,25yr,50yr,100yr,100plus,500yr
River Rch & RM=7002,36,13318.64
 4587.42  6494.6 6277.68 7153.68 8643.83 9718.71
River Rch & RM=7002,36, 13130.2
  4614.4 6525.67 6315.46 7196.18 8695.17 9776.72
River Rch & RM=7002,36,12941.76
 4752.92  6684.7 6509.48 7414.38 8958.8310074.64
River Rch & RM=7002,36,12753.33
 4768.64 6702.69  6531.5 7439.15 8988.7610108.45
River Rch & RM=7002,36,12552.96
 4807.25 6746.85 6585.62 7499.99 9062.2710191.53
River Rch & RM=7002,36,12352.59
 4817.07 6758.05 6599.37 7515.45 9080.9510212.64
River Rch & RM=7002,36,12105.57
 4854.32 6800.57 6651.59 7574.16 9151.8910292.81
River Rch & RM=7002,36,11858.55
 4863.47    6811 6664.41 7588.57  9169.310312.49
River Rch & RM=7002,36,11611.53
 4933.93 6891.23 6763.21 7699.62 9303.4910464.14
River Rch & RM=7002,36, 11364.5
 4945.01 6903.82 6778.75 7717.09 9324.5910487.99
River Rch & RM=7002,36,11117.48
 5206.69 7199.79 7145.95 8129.63 9823.0711051.46
River Rch & RM=7002,36,10870.46
 5214.45 7208.53 7156.86 8141.88 9837.8711068.19
River Rch & RM=7002,36,10623.44
 5249.37  7247.8 7205.89 8196.94  9904.411143.41
River Rch & RM=7002,36,   10185
 5336.53 7345.62 7328.31 8334.4110070.5111331.21
River Rch & RM=7002,36,9746.557
 5681.99 7730.44    7814 8879.4810729.1212075.99
River Rch & RM=7002,36,9308.115
 5863.82 7931.25 8069.92 9166.5211075.9512468.29
River Rch & RM=7002,36,8869.673
 5897.55 7968.36 8117.41 9219.78 11140.312541.08
River Rch & RM=7002,36,8431.231
 6077.85 8166.12 8371.39  9504.511484.3312930.27
River Rch & RM=7002,36,7992.789
 6098.75 8188.97 8400.84 9537.5111524.22 12975.4
River Rch & RM=7002,36,7554.347
 6113.95 8205.58 8422.25 9561.5111553.2213008.21
River Rch & RM=7002,36,7115.905
 8553.9110785.37   11875 13422.2 16218.1 18290.7
River Rch & RM=7002,36,6534.375
 8596.83 10829.411935.9613490.2216300.2918383.84
River Rch & RM=7002,36,6040.842
 8715.7610951.2112104.9213678.7216528.0718641.98
River Rch & RM=7002,36, 5547.31
 8736.87 10972.812134.9113712.1816568.49 18687.8
River Rch & RM=7002,36,5053.778
 9221.6611465.9412824.2114480.8317497.2619740.59
River Rch & RM=7002,36,4560.245
 9247.3911491.9812860.8214521.6417546.5719796.49
River Rch & RM=7002,36,4066.713
 9253.9711498.6412870.1814532.0817559.1819810.79
River Rch & RM=7002,36,2974.728
  9377.111623.03 13045.414727.3817795.1620078.33
River Rch & RM=7002,36,2494.405
 9518.49 11765.513246.6714951.6718066.1720385.61
River Rch & RM=7002,36,2092.583
 9929.6912177.6413832.4115604.1718854.5921279.67
River Rch & RM=7002,36,1984.946
 9931.4712179.4113834.9515606.99   1885821283.54
River Rch & RM=7002,36, 1576.78
 9940.9512188.8813848.4615622.0418876.1821304.16
River Rch & RM=7002,36,897.2621
10126.74   12374 14113.315916.9419232.52 21708.3
River Rch & RM=7002,36,368.2905
10133.8312381.0614123.41 15928.219246.1221723.73
River Rch & RM=7002,36,       0
10136.79   1238414127.6215932.8919251.7921730.15
Boundary for River Rch & Prof#=7002,36,1
Up Type= 0
Dn Type= 2
Boundary for River Rch & Prof#=7002,36,2
Up Type= 0
Dn Type= 2
Boundary for River Rch & Prof#=7002,36,2
Up Type= 0
Dn Type= 2
Boundary for River Rch & Prof#=7002,36,2
Up Type= 0
Dn Type= 2
Boundary for River Rch & Prof#=7002,36,2
Up Type= 0
Dn Type= 2
Boundary for River Rch & Prof#=7002,36,2
Up Type= 0
Dn Type= 2

--- 7002_ras.g01 (geometry) ---

Geom Title=7002
Program Version=4.10

River Reach=7002,36
Reach XY= 30
816506.127761605717872.760951184816456.987575801717631.984908794
816504.831821412717367.379512533816476.359222144717142.556746672
816829.137442888716974.521508131817134.451030048716723.312926066
817044.110122146716256.795677643817057.529034942716078.020480044
817297.714178594715650.506264465817978.863883824714815.935815702
818151.214698495714394.707186674818474.302865895713072.555325605
818406.138874117712777.762518161818159.956576298712667.668448891
817997.808617743712227.593248362818045.896531554 711473.50144378
817416.143143654710647.208103385817270.309810343710543.909492271
817353.374029222709903.606273394817499.476476999709732.277547848
817650.518143657709668.041436715817742.532032552 709728.80532562
 817812.84453258709902.416436725818139.331630738  709874.8726146
818207.637185067708950.311580515818408.327087492708214.904556535
818367.822028372707963.509307738818510.761199237707859.013658936
818894.441754787707742.694214507819065.931004318707366.536531316

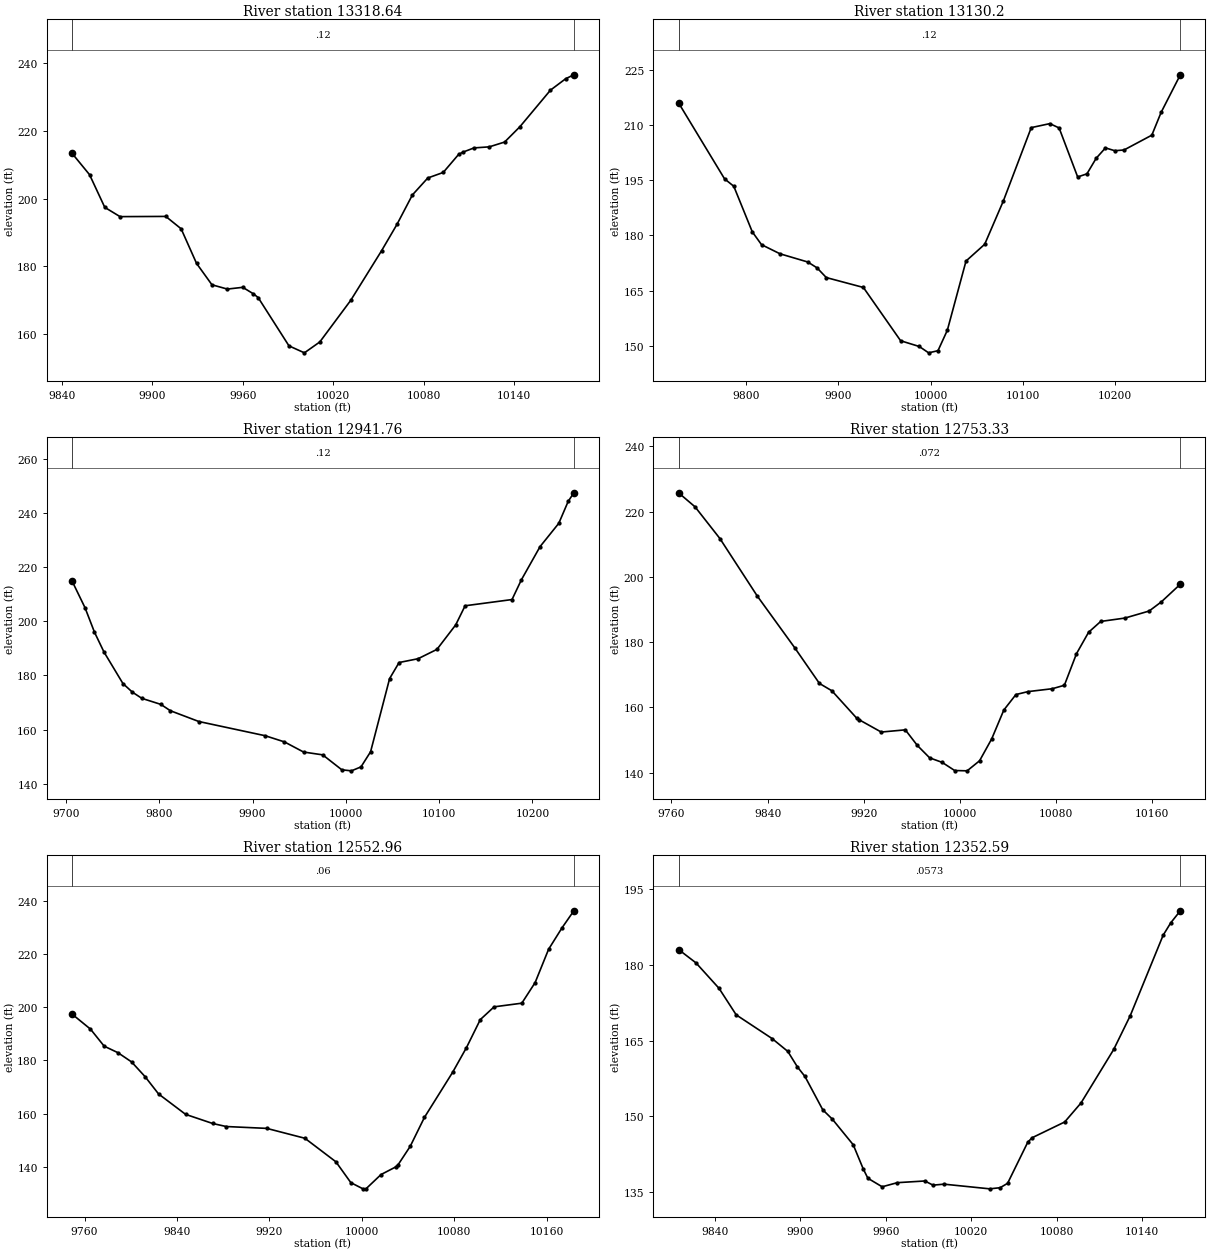
Type RM Length L Ch R = 1 ,13318.64,188.436700,188.436700,188.436700
XS GIS Cut Line= 6
816656.522157373717844.389944943816644.288678359717845.720220392
816591.858086728717853.684797259816506.859719112717871.550894075
816402.238726839717894.314893082816329.663806461717906.442702328
#Sta/Elev= 30
9846.807213.38729858.397207.08959868.507197.42829878.622194.69319908.966194.7551
9919.152191.09979929.371180.88429939.589174.55739949.808 173.2919960.026173.8069
9967.153171.87129970.245170.78139990.682156.515110000.92154.453410011.15157.6737
10031.61169.934910052.08184.592110062.31192.386210072.55201.097710082.78206.1127
10093.01207.745510103.24213.085110106.07213.745210113.41214.992210123.56215.3065
10133.71216.722610143.86221.244810164.15232.062910174.27 235.44310179.66236.5986
#Mann= 3 , 0 , 0
9846.807    0.12       09846.807    0.12       010179.66    0.12       0
#XS Ineff= 2 , 0
       0                               0
Bank Sta=9846.807,10179.66
Exp/Cntr=0.3,0.1

Type RM Length L Ch R = 1 , 13130.2,188.436800,188.436800,188.436800
XS GIS Cut Line= 6
816734.790340117717673.332009807816667.878495355  717671.5487876
816616.948754041 717672.45132429816522.696288858717679.801042566
816339.399698811717705.277361649 816194.23313089717716.937052632
#Sta/Elev= 30
9727.259216.00219777.067195.3523 9787.07193.33289807.075180.95459817.077 177.471
 9837.08174.99229867.148 172.7599877.178171.16989887.208168.5306 9927.33165.8452
9967.649151.36489987.853149.80329997.955148.080810008.07148.659810018.19154.2123
10038.42 173.02210058.64 177.57810078.79189.319610109.02209.269910129.16210.3567
10139.19209.178310159.26195.867910169.29196.710110179.33200.951210189.36203.7645
 10199.4202.994810209.43203.193410239.53207.219510249.57213.397510270.38223.6268
#Mann= 3 , 0 , 0
9727.259    0.12       09727.259    0.12       010270.38    0.12       0
#XS Ineff= 2 , 0
       0                               0
Bank Sta=9727.259,10270.38
Exp/Cntr=0.3,0.1

Type RM Length L Ch R = 1 ,12941.76,188.436700,188.436700,188.436700
XS GIS Cut Line= 6
816758.639823281717558.212505523816564.908756564717523.087100147
816437.189625052717493.770411996816385.741930631717484.441384707
816309.475675163717475.682023096816228.912205356717469.638933939
#Sta/Elev= 30
9706.562214.82969720.424204.98539730.587195.9277 9740.75188.62659761.076176.9767
 9771.24173.78639781.403171.50499801.729169.28019811.892166.94419842.381162.9621
9913.618157.70369934.137155.43379954.657151.68859975.176150.64369995.695145.1184
10005.96144.744510016.22146.208510026.48151.782410046.88178.814710057.04184.7412
10077.37186.140810097.59189.589210117.72198.641910127.79205.695410178.06207.9917
10188.09215.269810208.15227.5532 10228.2236.147810238.23244.219810244.34247.4158
#Mann= 3 , 0 , 0
9706.562    0.12       09706.562    0.12       010244.34    0.12       0
#XS Ineff= 2 , 0
       0                               0
Bank Sta=9706.562,10244.34
Exp/Cntr=0.3,0.1

Type RM Length L Ch R = 1 ,12753.33,200.367800,200.367800,200.367800
XS GIS Cut Line= 6
816728.284710606717353.977913143816575.506932815717313.005690919
816530.368043949 717309.53346868 816486.61804389717322.033468695
816466.479155054717324.811246456816319.256932825717343.561246455
#Sta/Elev= 30
9765.882225.79629779.636221.48419800.343211.75979831.403194.16379862.463 178.368
 9883.17167.36279893.523165.1157 9914.23156.7036 9916.36  156.219934.597152.4677
9954.656153.14159964.685148.34879974.914144.55949985.314 143.1749995.714140.6821
10006.11140.580510016.46143.665110026.56150.372110036.65159.214310046.73163.9621
10056.81164.863510076.98165.745810087.06166.804510097.14176.486610107.22183.0495
 10117.3186.366910137.46187.401710157.62189.5584 10167.7192.344310183.57197.7734
#Mann= 3 , 0 , 0
9765.882   0.072       09765.882   0.072       010183.57   0.072       0
#XS Ineff= 2 , 0
       0                               0
Bank Sta=9765.882,10183.57
Exp/Cntr=0.3,0.1

Type RM Length L Ch R = 1 ,12552.96,200.367900,200.367900,200.367900
XS GIS Cut Line= 6
816698.412030786 717260.74646421 816527.42474427 717155.41992372
816502.937389799717137.878694524816464.717775259717105.948741214
816430.742639741717081.433796853816336.238396317717021.796871642
#Sta/Elev= 30
9749.145197.3556 9765.08191.71839776.961185.31279788.841 182.872 9800.63179.4143
9812.337173.87819824.044167.36519847.457159.70399870.871156.27879882.577155.1386
9917.698154.4425  9950.7150.73269977.564141.89059990.497134.0614   10001131.7371
10003.68131.779110016.61137.096810029.55140.007610031.53 140.86810041.89147.6931
10054.23158.586810078.67175.541610090.62184.799410102.57195.293310114.52200.0886
10138.51201.457210150.02209.179110161.69221.702410173.35229.786710183.57 236.164
#Mann= 3 , 0 , 0
9749.145    0.06       09749.145    0.06       010183.57    0.06       0
#XS Ineff= 2 , 0
       0                               0
Bank Sta=9749.145,10183.57
Exp/Cntr=0.3,0.1

Type RM Length L Ch R = 1 ,12352.59,247.021400,247.021400,247.021400
XS GIS Cut Line= 6
816721.896533923717208.567119734816661.270821691717119.125482574
816653.631932795717080.931038141816671.687488377717037.181038126
816661.270821691717008.708815917816554.533734913716941.610967222
#Sta/Elev= 30
9814.274183.09219826.565180.43619842.745175.39439854.825170.13499880.034165.4406
9891.068162.89899897.857159.81019903.148157.9248 9915.68151.31179922.326 149.485
9937.074144.38749944.077139.62199947.379 137.7479957.411136.05789968.092 136.874
9987.423137.20849993.172136.3817 10000.9136.577110033.03135.650610040.37135.8757
10045.61136.751910059.75144.879110062.74145.766510085.72148.9018 10097.2152.6714
10120.21163.286610131.78169.954110154.92185.910710160.28 188.37710167.02190.7686
#Mann= 3 , 0 , 0
9814.274  0.0573       09814.274  0.0573       010167.02  0.0573       0
#XS Ineff= 2 , 0
       0                               0
Bank Sta=9814.274,10167.02
Exp/Cntr=0.3,0.1

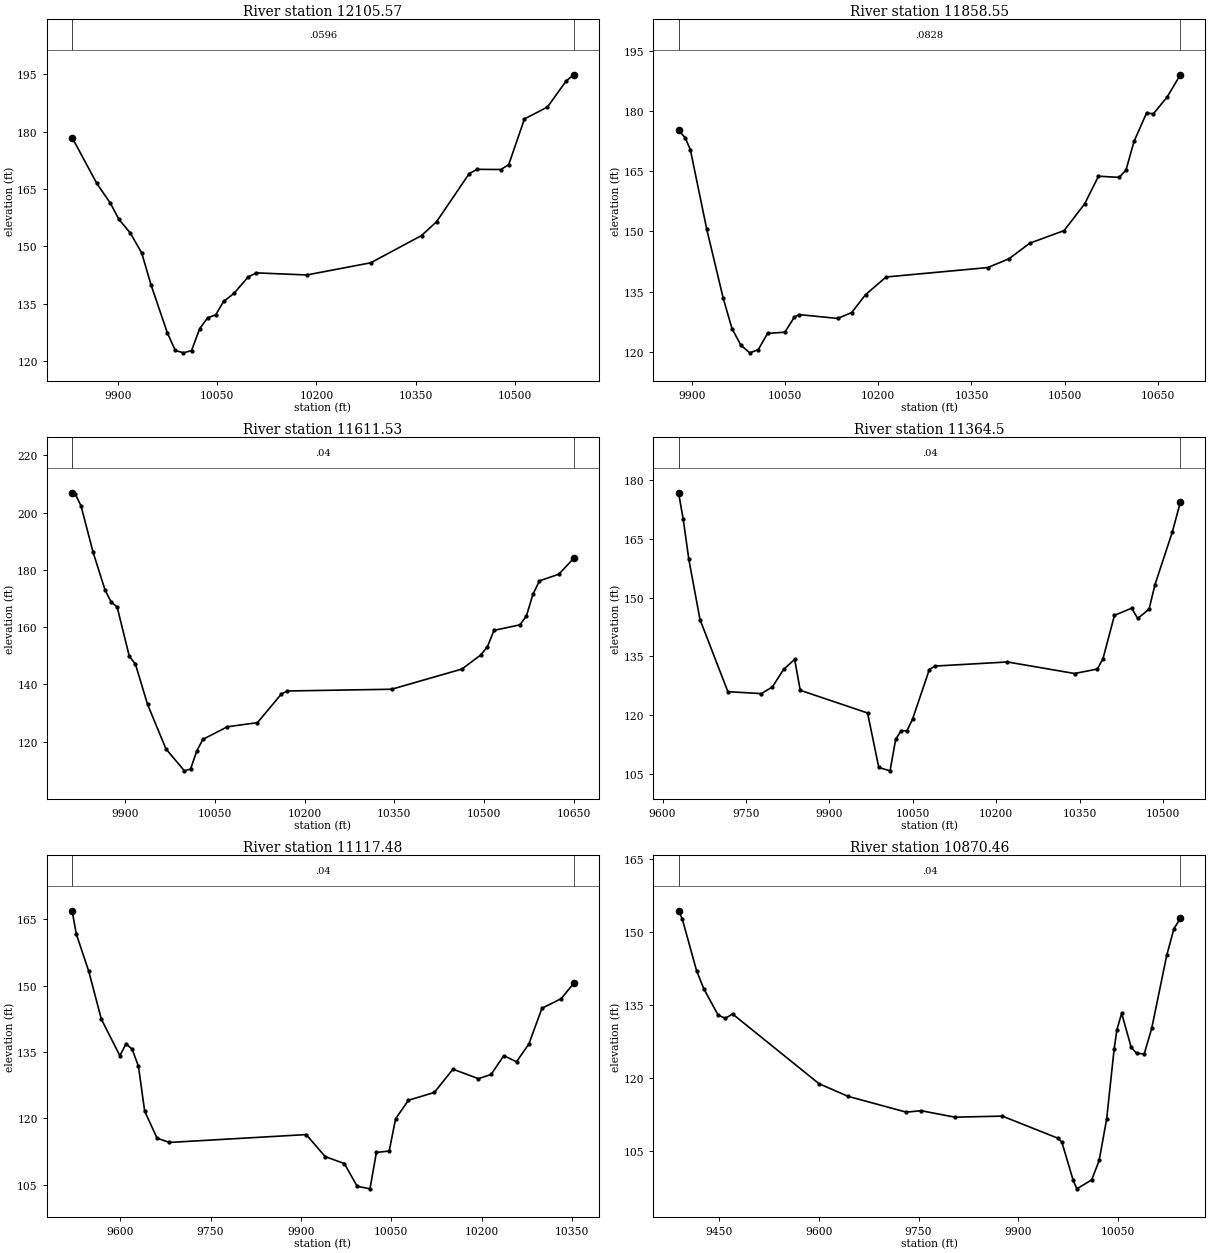
Type RM Length L Ch R = 1 ,12105.57,247.021300,247.021300,247.021300
XS GIS Cut Line= 6
816988.014187128717070.829383829816797.690334235716808.336338926
816717.832649771716720.591980076816649.624582322716662.156786525
816591.387410047716619.768571549816460.474232991716539.314063055
#Sta/Elev= 30
9830.592178.42969867.905166.48589888.678 161.2429901.345157.09479918.622153.5139
9935.898 148.2979949.993139.9803 9974.52127.52199986.783122.86999999.045122.2566
10011.21122.843910023.39128.517510035.56131.401210047.74132.172510059.92135.7113
10075.22137.743610096.66142.022910109.14143.122310185.34142.572810282.03 145.746
10358.91152.858910381.54156.447110431.01169.025310443.08170.132510478.79170.0829
10490.69171.350410514.49183.283510549.26186.386710577.86193.257210589.18 194.801
#Mann= 3 , 0 , 0
9830.592  0.0596       09830.592  0.0596       010589.18  0.0596       0
#XS Ineff= 2 , 0
       0                               0
Bank Sta=9830.592,10589.18
Exp/Cntr=0.3,0.1

Type RM Length L Ch R = 1 ,11858.55,247.021400,247.021400,247.021400
XS GIS Cut Line= 6
817169.939537129716861.559560374817108.779175551  716809.1285286
817051.281368876716750.287309014816991.003354293716705.788870139
816943.484193432716680.882880701816475.820390123716463.280830014
#Sta/Elev= 30
9878.646175.19939889.245173.31269897.666170.3402 9923.86150.64299950.508133.3584
 9964.66125.78719978.973121.62669993.286119.732410006.93120.514110021.92124.5703
10049.78124.874510065.06128.643510072.78129.253310134.65128.304310157.23129.7623
10179.56134.220810212.57138.6263 10376.3140.974410410.67143.193810443.82147.0492
10499.08150.185310532.23156.867910554.34163.727510587.49163.444510598.54165.2111
10611.53172.386510631.69179.465910642.75179.279710664.85 183.45610686.05188.9953
#Mann= 3 , 0 , 0
9878.646  0.0828       09878.646  0.0828       010686.05  0.0828       0
#XS Ineff= 2 , 0
       0                               0
Bank Sta=9878.646,10686.05
Exp/Cntr=0.3,0.1

Type RM Length L Ch R = 1 ,11611.53,247.021300,247.021300,247.021300
XS GIS Cut Line= 6
817289.881833741716528.441687249817224.607646363716535.151436169
816989.527801352716582.296545694816900.547085393716578.499087764
816748.194990919716540.076120826816482.118564169716432.076240434
#Sta/Elev= 30
9810.991206.93489815.898206.65949825.951202.35839846.056186.22589866.162172.9736
9876.215168.82489886.376 167.0579906.709149.81279916.876147.12139937.244133.0074
9968.114117.42249998.984109.793410009.26110.418610019.53116.7227 10029.8  120.78
 10070.7 125.18210121.11126.631510161.14136.653710171.17137.691210345.49138.2994
10463.14145.354610494.99150.340710505.84153.2031 10516.7158.862810560.11160.7997
10570.97163.918410581.82171.441610592.67176.145110625.35178.511810650.31184.1117
#Mann= 3 , 0 , 0
9810.991    0.04       09810.991    0.04       010650.31    0.04       0
#XS Ineff= 2 , 0
       0                               0
Bank Sta=9810.991,10650.31
Exp/Cntr=0.3,0.1

Type RM Length L Ch R = 1 , 11364.5,247.021400,247.021400,247.021400
XS GIS Cut Line= 6
817423.424658498716303.864223596817222.726332976716297.517161025
816958.271843274 716332.30077894816849.123760942716335.894883476
816724.845148359716322.879636216816531.170296622716273.135428783
#Sta/Elev= 30
9628.701176.76449637.197169.9441 9647.23159.74099667.298144.3848 9717.41125.9725
9777.432125.47439797.443127.16799817.453131.63559837.487134.20899847.522126.3222
9968.578120.52829988.799106.607610009.03105.751410019.15113.818410029.26 116.032
10039.38115.948110049.48 118.961 10079.7131.628210089.78132.508210219.98133.5565
 10340.9130.606610381.75131.751410391.96134.420410412.51145.463610443.49147.2839
10454.37144.657510474.78147.048310485.21153.2248 10516.5166.708110530.96174.3411
#Mann= 3 , 0 , 0
9628.701    0.04       09628.701    0.04       010530.96    0.04       0
#XS Ineff= 2 , 0
       0                               0
Bank Sta=9628.701,10530.96
Exp/Cntr=0.3,0.1

Type RM Length L Ch R = 1 ,11117.48,247.021300,247.021300,247.021300
XS GIS Cut Line= 6
817521.831799954716198.667333919817221.147805916716125.848246666
817159.222720378716109.021636146817110.410463363716093.664029272
 816991.38259526716050.914288773816725.044068722 715960.61967578
#Sta/Elev= 30
9520.329166.95669527.402161.67249548.107153.24159568.786142.48789599.623134.1923
9609.902136.88869620.181135.6168 9630.46131.77489640.739121.66939661.297115.5485
9681.855114.58019908.801116.35799940.251111.36999972.032109.8075 9993.26104.6805
10014.54104.090410025.17112.311310046.43112.644610057.06119.924310078.27124.1141
10121.42125.890510152.13 131.14510194.34129.000710215.46 129.94310236.54134.2016
10257.64 132.82910278.15136.828910299.85144.919910331.58147.075510352.77150.5912
#Mann= 3 , 0 , 0
9520.329    0.04       09520.329    0.04       010352.77    0.04       0
#XS Ineff= 2 , 0
       0                               0
Bank Sta=9520.329,10352.77
Exp/Cntr=0.3,0.1

Type RM Length L Ch R = 1 ,10870.46,247.021400,247.021400,247.021400
XS GIS Cut Line= 6
817730.126995185716110.809816964817571.928607234716045.585390888
 817444.31603512715990.026512024817341.526409026715941.464817306
817150.992345733715845.401734989817046.930909224715790.517620643
#Sta/Elev= 30
  9388.8154.30679394.346152.66329415.979141.98869426.796138.29859448.429132.8619
9459.245132.22089470.062133.11519600.194118.7882 9643.82116.19719731.522112.9465
9753.642113.24329804.507111.91989876.086112.12889960.435107.54829965.676106.7167
 9982.6598.931679988.07397.1964310010.4799.0369510021.67103.019210032.94111.5285
10044.24125.925310048.46129.915110055.55133.2637 10069.9126.244610078.16125.0469
10089.47 124.90210100.77130.175610123.38145.1629 10134.2150.627310143.81152.7261
#Mann= 3 , 0 , 0
  9388.8    0.04       0  9388.8    0.04       010143.81    0.04       0
#XS Ineff= 2 , 0
       0                               0
Bank Sta=9388.8,10143.81
Exp/Cntr=0.3,0.1

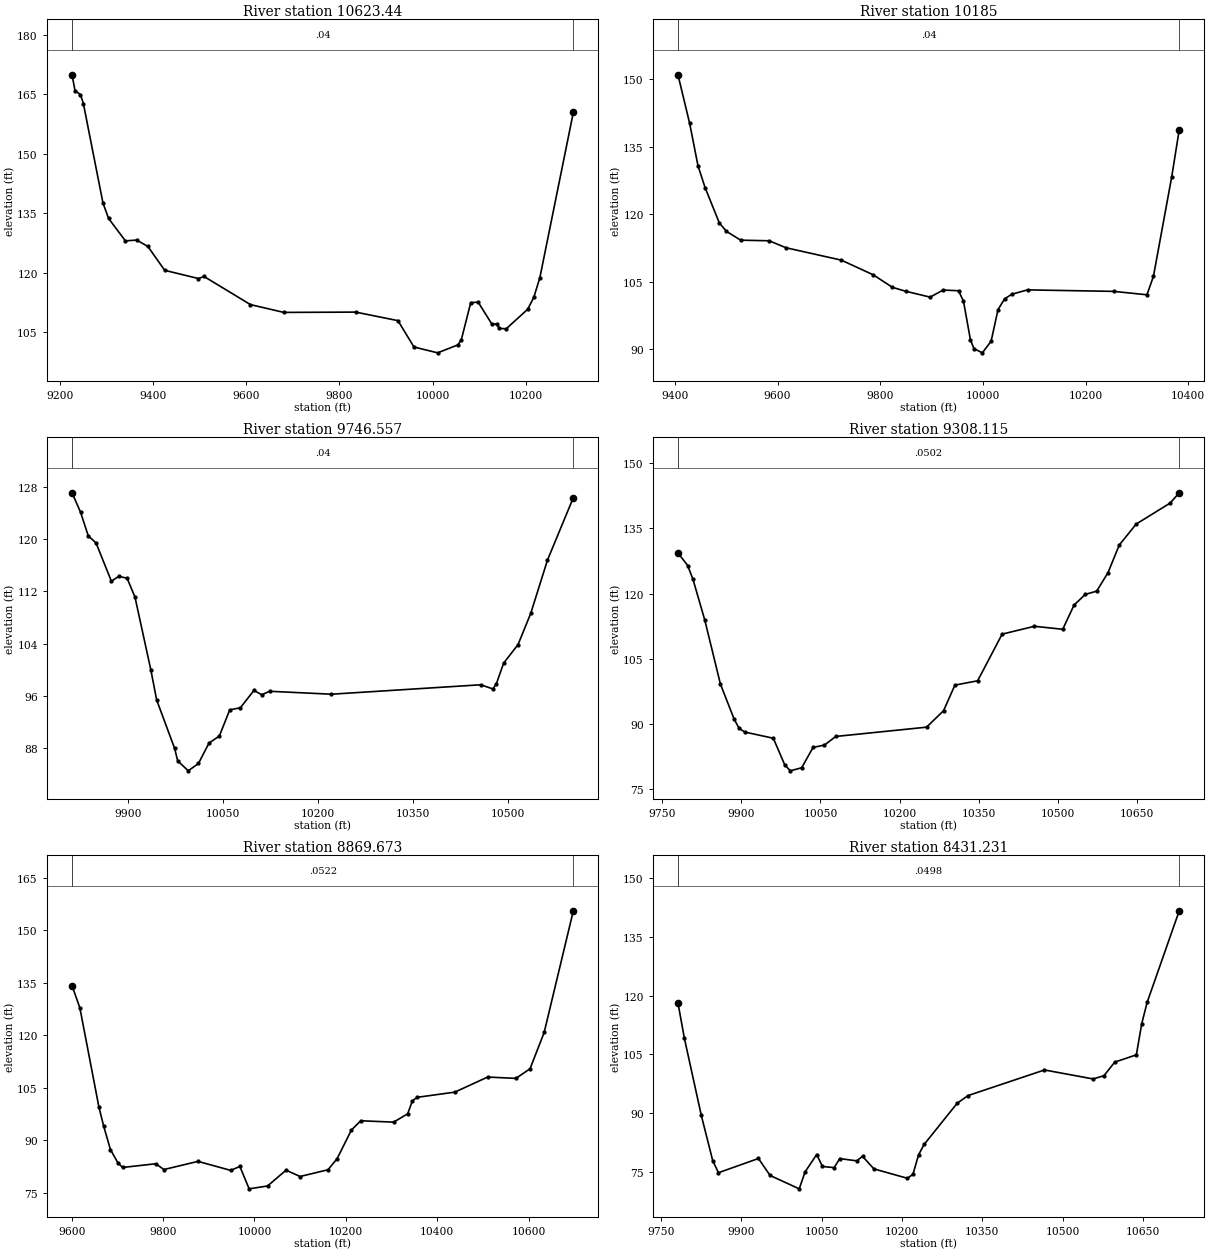
Type RM Length L Ch R = 1 ,10623.44,438.442000,438.442000,438.442000
XS GIS Cut Line= 6
 817900.04673471716108.561436818817337.428229123715730.410204798
817302.706006855715681.799093693817300.101840228715612.354649231
817290.553229123715574.160204798817119.264037395715422.651115544
#Sta/Elev= 30
9226.315169.89259232.699165.87959244.444164.89799250.625162.6456 9292.64137.5952
9304.689133.67839340.835128.02679364.933 128.2279389.031126.61899425.177120.5993
9497.471118.5368 9509.52119.05049609.155111.95949680.861109.99329834.839110.0728
9925.589107.91779959.998101.271410010.7899.8037710054.47101.819310061.63103.1146
10081.78  112.4610097.77112.569510127.61  106.9610137.63107.1187 10142.8105.9553
10157.99105.874510204.06110.7941 10217.2113.815610230.09 118.73810301.95 160.419
#Mann= 3 , 0 , 0
9226.315    0.04       09226.315    0.04       010301.95    0.04       0
#XS Ineff= 2 , 0
       0                10099.29       0
Bank Sta=9226.315,10301.95
Exp/Cntr=0.3,0.1

Type RM Length L Ch R = 1 ,   10185,438.442100,438.442100,438.442100
XS GIS Cut Line= 6
817943.145957149715770.795020627817724.175914258715555.728491828
817691.623830974715436.370852932817650.616339903715370.465956585
817432.983891236715176.657271722817295.301639005715066.000267981
#Sta/Elev= 30
9406.105150.99699428.906140.19339445.131130.78489458.997125.92829486.648118.1114
9500.595 116.2259528.326114.27369583.789114.13889616.569112.59029724.191 109.846
9786.382106.58679823.956103.79969849.325102.93999897.291101.62669922.597103.1997
9952.558103.04679962.243100.72769975.67492.201359982.519 90.1957    999989.25804
10016.0391.84014 10029.598.8495910042.26101.240610056.45102.272810087.02103.2381
10255.13102.902710319.56102.148510332.22106.234510367.83128.3463 10382.5138.8276
#Mann= 3 , 0 , 0
9406.105    0.04       09406.105    0.04       0 10382.5    0.04       0
#XS Ineff= 2 , 0
       0                10219.49       0
Bank Sta=9406.105,10382.5
Exp/Cntr=0.3,0.1

Type RM Length L Ch R = 1 ,9746.557,438.442000,438.442000,438.442000
XS GIS Cut Line= 6
818026.129796844715093.076225535817965.725969078715051.261430057
817749.391738776714889.153350761817671.973018758 714835.91996018
817472.884751076714710.847602943817369.341689192714651.933562069
#Sta/Elev= 30
9811.083127.05179824.619124.06419836.782120.45119848.944119.40079873.269113.5317
9884.548114.27069897.981114.01469910.504111.11849935.551100.00519944.78595.39568
9973.12188.004059978.00886.10398 9994.6284.56873 10010.885.6913210027.4588.80324
10043.8589.8939110060.2693.8857710077.0394.2066410098.4796.8519610110.8496.19308
10123.2196.72532 10220.996.2764210456.7997.7186610476.0197.0870410481.5197.87158
10493.08101.037110515.81103.8651 10535.9108.648910562.27116.773410603.12126.3094
#Mann= 3 , 0 , 0
9811.083    0.04       09811.083    0.04       010603.12    0.04       0
#XS Ineff= 2 , 0
       0                               0
Bank Sta=9811.083,10603.12
Exp/Cntr=0.3,0.1

Type RM Length L Ch R = 1 ,9308.115,438.442100,438.442100,438.442100
XS GIS Cut Line= 6
818272.028990993714675.998404125818088.623936843714599.537310575
818067.413661659714591.183361386 817574.08991282714393.926634975
 817410.01293213 714330.63795274817388.653414431714322.771012341
#Sta/Elev= 30
9779.499129.34689797.948 126.4519808.081123.23789830.451113.86979860.057 99.1547
9886.04491.090439895.45688.97287 9906.2988.094039960.462 86.6705  9982.180.56065
9992.85179.1624310014.3779.8812810035.9184.5548910057.45 85.092110078.9987.08013
 10251.389.2191710283.6193.0175110305.1598.9086910348.2399.8974810394.74110.6466
10455.93112.452410509.78111.763510531.32117.353310552.76119.8072 10574.2120.5454
10595.63124.792810617.07131.162510649.22136.0068 10713.5140.820510730.92143.2022
#Mann= 3 , 0 , 0
9779.499  0.0502       09779.499  0.0502       010730.92  0.0502       0
#XS Ineff= 2 , 0
       0                               0
Bank Sta=9779.499,10730.92
Exp/Cntr=0.3,0.1

Type RM Length L Ch R = 1 ,8869.673,438.442000,438.442000,438.442000
XS GIS Cut Line= 6
818591.486268296714268.236526457818385.918195713714211.894144783
818268.750831032714185.817189771818143.705825506 714168.63198003
818019.310226777714143.791605479817522.989970286714023.761265702
#Sta/Elev= 30
9600.898 134.1679618.067127.76659659.72399.433599670.13793.989269684.86887.30466
9701.21183.507839711.55782.175319783.97583.239099801.94181.58264 9876.4783.91481
9947.98581.344189968.18882.467159988.39176.0662610028.7576.88396 10069.281.40726
10099.7979.5921810160.9781.52478   1018184.7061710212.1392.8688510232.6695.52742
10304.5295.1379310335.3497.5216310345.63101.226810355.93102.229910438.31103.7123
10510.39 108.02810572.17 107.64510603.06110.404210633.95120.7671 10697.8155.5662
#Mann= 3 , 0 , 0
9600.898  0.0522       09600.898  0.0522       0 10697.8  0.0522       0
#XS Ineff= 2 , 0
       0                               0
Bank Sta=9600.898,10697.8
Exp/Cntr=0.3,0.1

Type RM Length L Ch R = 1 ,8431.231,438.442000,438.442000,438.442000
XS GIS Cut Line= 6
818506.443889162713828.875137031818369.630756805713780.457605455
818235.631908478713723.579467908818067.913136964713670.374067016
817880.715827966 713631.56077818817605.283047377713598.002704621
#Sta/Elev= 30
9782.054118.13789794.046109.11729825.63189.428349846.93477.886599857.58574.80113
9932.247 78.43629953.99374.0988610008.3770.6881710019.2274.9909210040.9279.45474
10051.7776.3937110073.45 76.107610084.0678.4039810115.8877.8346410126.48 78.9988
10147.6975.7856810210.2473.3786110220.6474.3925410231.0579.3645310241.4582.01901
10303.0692.5308210323.5694.5060910466.04101.036210556.9498.7422110577.0899.57718
10597.22103.043110637.51 104.89310647.57 112.85810657.61118.282310717.58141.6763
#Mann= 3 , 0 , 0
9782.054  0.0498       09782.054  0.0498       010717.58  0.0498       0
#XS Ineff= 2 , 0
       0                               0
Bank Sta=9782.054,10717.58
Exp/Cntr=0.3,0.1

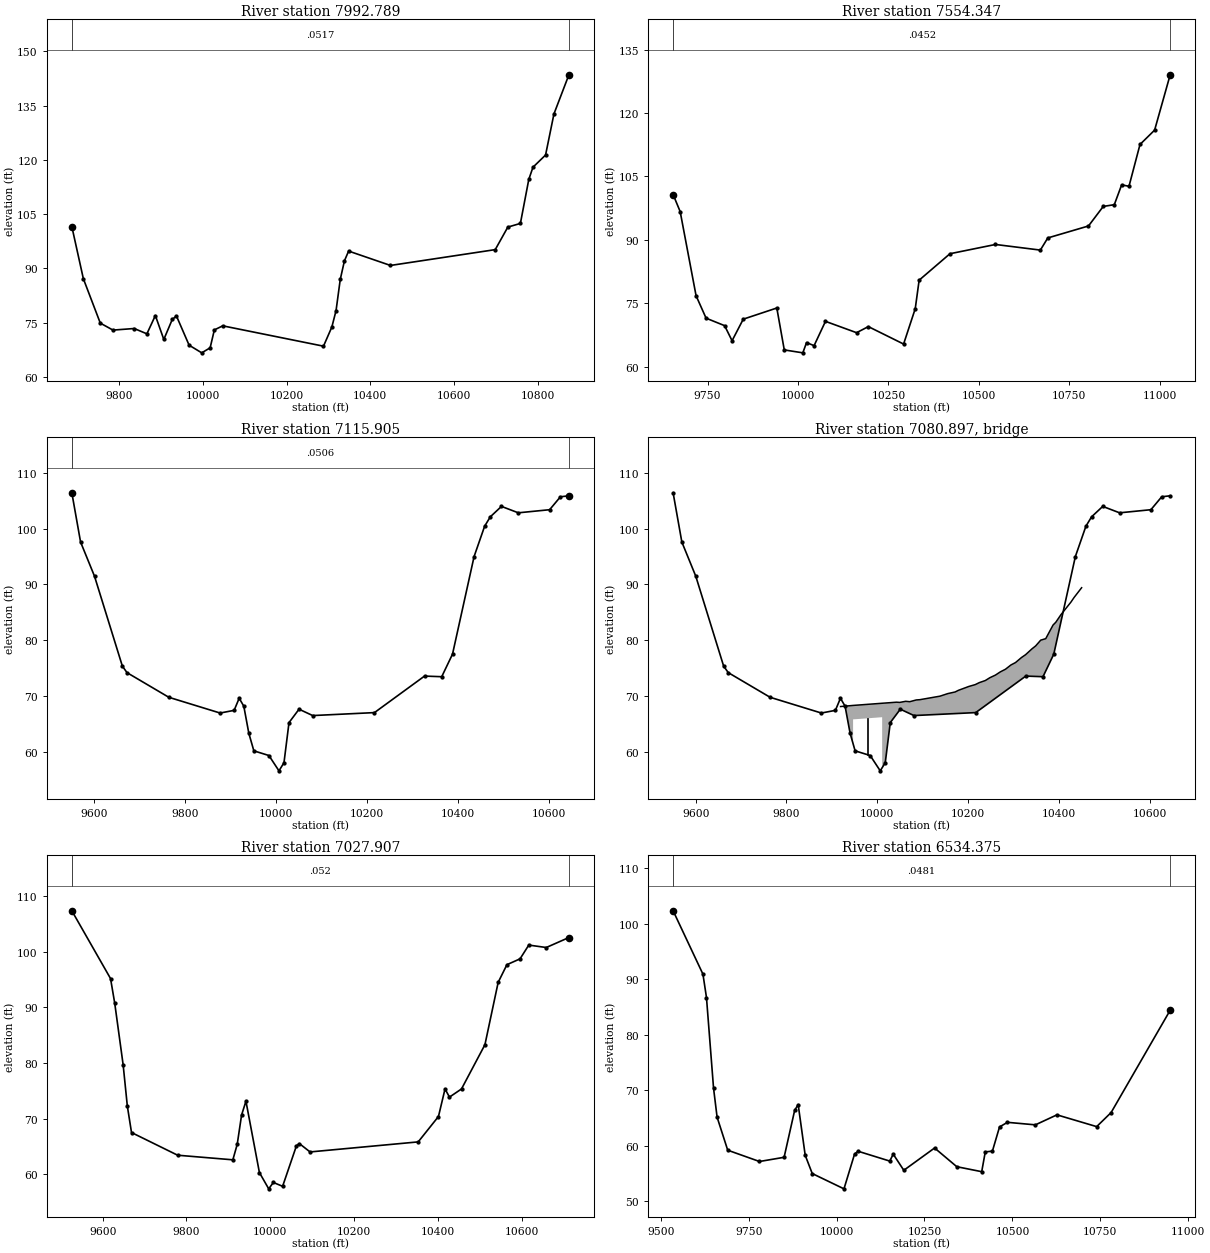
Type RM Length L Ch R = 1 ,7992.789,438.442100,438.442100,438.442100
XS GIS Cut Line= 6
818712.212039696713376.020752894818420.574346523713333.170077572
818197.459837618713313.039310199 818072.55417093 713307.20244429
817919.477208643713308.911031877817529.338352191713332.433391746
#Sta/Elev= 30
9687.014101.56669714.55787.161419755.04374.895589785.40872.969729836.01673.40857
9866.38171.943589886.62476.994519906.81570.388779926.969 75.90579937.04676.86381
9967.277 68.80179997.44766.6895710017.5368.0787610027.5773.0260710047.6574.14876
10288.3868.5284410308.4173.8378310318.4278.3665310328.4386.9576510338.4392.10161
10348.43 94.798310448.4590.8288610698.8195.1995710728.87101.423910758.93102.4372
10778.97114.5926   10789117.964210819.06121.3279 10839.1132.682110874.84 143.497
#Mann= 3 , 0 , 0
9687.014  0.0517       09687.014  0.0517       010874.84  0.0517       0
#XS Ineff= 2 , 0
       09883.731                       0
Bank Sta=9687.014,10874.84
Exp/Cntr=0.3,0.1

Type RM Length L Ch R = 1 ,7554.347,438.442000,438.442000,438.442000
XS GIS Cut Line= 6
 818784.10591133712831.637139815 818384.02540687712927.458613201
818108.104077208 713038.23331296817864.474918118713114.172539089
817621.096705263713166.781802428817462.416897903713191.523616407
#Sta/Elev= 30
9654.749100.69849674.29396.66006 9718.2576.755019745.89671.447039797.09969.67665
9817.71266.108749848.63171.213199941.38973.852679962.00263.9373410013.2963.24581
10023.5465.6734410044.3964.9448310075.8670.6953910161.8268.0119210194.3569.45273
10291.7765.32507   1032473.7013110334.7480.4360710419.9686.6937510545.7488.88423
10669.7787.5532510690.3390.4303810802.8293.26227 10843.697.8839210874.1598.29824
10894.44102.987510914.73102.651410945.16112.541610985.56115.936411028.58129.0312
#Mann= 3 , 0 , 0
9654.749  0.0452       09654.749  0.0452       011028.58  0.0452       0
#XS Ineff= 2 , 0
       0 9924.21                       0
Bank Sta=9654.749,11028.58
Exp/Cntr=0.3,0.1

Type RM Length L Ch R = 1 ,7115.905,87.997200,87.997200,87.997200
XS GIS Cut Line= 6
818583.812632024712536.278768331818322.011409312712591.949143291
818224.212101907712616.022818953817962.410879225712739.400406674
817840.537896186712804.098409995817589.268906534712965.091115952
#Sta/Elev= 30
9550.402106.41579569.63597.596869600.30691.472249661.64775.369419671.87174.20024
9763.88369.78864 9876.7766.967789907.66567.447069918.77569.617719928.95968.19228
9940.01463.340979951.06960.195369984.23359.3587510006.34 56.6144 10017.458.06935
10028.4565.2531810050.5667.6538210080.5866.5145510216.5867.0442410326.7773.58587
10364.6373.4730110388.3877.5122110435.8994.9970210459.06100.421710471.52102.1054
10496.13103.976310533.21102.827710602.16103.383810625.91105.696810644.59105.8768
#Mann= 3 , 0 , 0
9550.402  0.0506       09550.402  0.0506       010644.59  0.0506       0
#XS Ineff= 2 , 0
       09920.401        10046.91       0
Bank Sta=9550.402,10644.59
Exp/Cntr=0.3,0.1

Type RM Length L Ch R = 3 ,7080.897,,,
BEGIN DESCRIPTION:
END DESCRIPTION:
Bridge Culvert--1,0,-1,-1, 0
Deck Dist Width WeirC Skew NumUp NumDn MinLoCord MaxHiCord MaxSubmerge Is_Ogee
35.998600,16.000000,2.6,0, 37, 34, , , 0.95, 0, 0,0,,
 9919.06 9946.55 9946.5510010.5510010.5510042.2410049.1610062.3810071.3310085.55
10093.5010137.8510155.0610171.1010178.2310201.4010215.4410224.5710237.6210247.74
10259.7910270.8710281.9610294.0810304.1310317.2510326.3010340.4210348.4710359.56
10370.6410386.7710392.8110403.9010426.0710433.1110449.64
   68.13   68.33   68.33   68.72   68.72   68.91   68.87   69.07   69.00   69.31
   69.36   69.99   70.45   70.74   71.03   71.73   72.06   72.42   72.79   73.30
   73.76   74.35   74.81   75.58   76.01   76.91   77.42   78.47   78.99   80.02
   80.29   82.73   83.23   84.56   86.83   87.67   89.41
 -931.87 -931.67   65.83   66.22 -931.28 -931.09 -931.13 -930.93 -931.00 -930.69
 -930.64 -930.01 -929.55 -929.26 -928.97 -928.27 -927.94 -927.58 -927.21 -926.70
 -926.24 -925.65 -925.19 -924.42 -923.99 -923.09 -922.58 -921.53 -921.01 -919.98
 -919.71 -917.27 -916.77 -915.44 -913.17 -912.33 -910.59
 9919.06 9967.35 9967.3510031.3510031.3510042.2410049.1610062.3810071.3310085.55
10093.5010137.8510155.0610171.1010178.2310201.4010215.4410224.5710237.6210281.96
10294.0810304.1310317.2510326.3010340.4210348.4710359.5610370.6410386.7710392.81
10403.9010426.0710433.1110449.64
   68.13   68.46   68.46   68.84   68.84   68.91   68.87   69.07   69.00   69.31
   69.36   69.99   70.45   70.74   71.03   71.73   72.06   72.42   72.79   74.81
   75.58   76.01   76.91   77.42   78.47   78.99   80.02   80.29   82.73   83.23
   84.56   86.83   87.67   89.41
 -931.87 -931.54   65.96   66.34 -931.16 -931.09 -931.13 -930.93 -931.00 -930.69
 -930.64 -930.01 -929.55 -929.26 -928.97 -928.27 -927.94 -927.58 -927.21 -925.19
 -924.42 -923.99 -923.09 -922.58 -921.53 -921.01 -919.98 -919.71 -917.27 -916.77
 -915.44 -913.17 -912.33 -910.59
Pier Skew, UpSta & Num, DnSta & Num=  ,9978.55, 2 ,9999.35, 2 , 0 , 0 , 0 ,,
    3.00    3.00
 -931.47   68.53
    3.00    3.00
 -931.35   68.65
BR Coef=-1 , 0 , 0 ,, 0 ,,,0.8,0,1,0,
WSPro=,,,, 1 ,,,, 0 ,,,, 0 ,,,,-1 ,-1 ,-1 , 0 , 0 , 0 , 0 , 0
BC Design=,, 0 ,, 0 ,,,,,,

Type RM Length L Ch R = 1 ,7027.907,493.532400,493.532400,493.532400
XS GIS Cut Line= 6
818597.354074627712503.177464306818349.094294399 712513.70969741
818239.258149236712527.251139969818167.961794124712548.148347497
817759.827715756712716.993467651817463.287511866712811.964174314
#Sta/Elev= 30
9526.251107.32329618.688 95.14799628.69790.705759648.71579.690659658.72472.27537
9668.73367.501939778.859 63.4288 9910.6862.601969921.10165.376689931.52270.63755
9941.94273.135099974.08660.311139996.30657.3903210007.37 58.535410029.4957.84416
10062.6465.1462110069.6765.5066910095.0264.0172510353.2265.8216310401.5870.38036
10417.2775.3327510427.85  73.863 10456.675.3291510512.5283.2713610544.1494.47436
10565.0397.6415310596.3598.6915510617.24101.162210659.01100.727610713.02102.5203
#Mann= 3 , 0 , 0
9526.251   0.052       09526.251   0.052       010713.02   0.052       0
#XS Ineff= 2 , 0
       09944.743        10061.74       0
Bank Sta=9526.251,10713.02
Exp/Cntr=0.3,0.1

Type RM Length L Ch R = 1 ,6534.375,493.532500,493.532500,493.532500
XS GIS Cut Line= 6
818449.043523992712076.011079919818191.541083321712103.961422364
817834.383172939712095.819458338817630.792966454712113.673948383
817361.442469626712164.012585452817051.544183009 712237.31531331
#Sta/Elev= 30
9535.083   102.39619.91890.899689629.98586.691169650.11870.366849660.18565.16542
9690.38559.224929780.68557.191799850.74957.947339880.76266.395559890.76667.43469
9910.77358.30643 9930.7855.0229110021.0252.2729110051.0958.5206610061.1259.03587
10151.1257.2689810161.13 58.506810191.18 55.609410278.7159.6201210341.89 56.2539
10412.7155.3591910422.8458.9211510443.1159.0519410463.3763.4069910485.8664.23914
10565.3763.7855610626.6265.5854810739.6363.4671110780.7465.99918 10948.784.40757
#Mann= 3 , 0 , 0
9535.083  0.0481       09535.083  0.0481       0 10948.7  0.0481       0
#XS Ineff= 2 , 0
       09890.834                       0
Bank Sta=9535.083,10948.7
Exp/Cntr=0.3,0.1

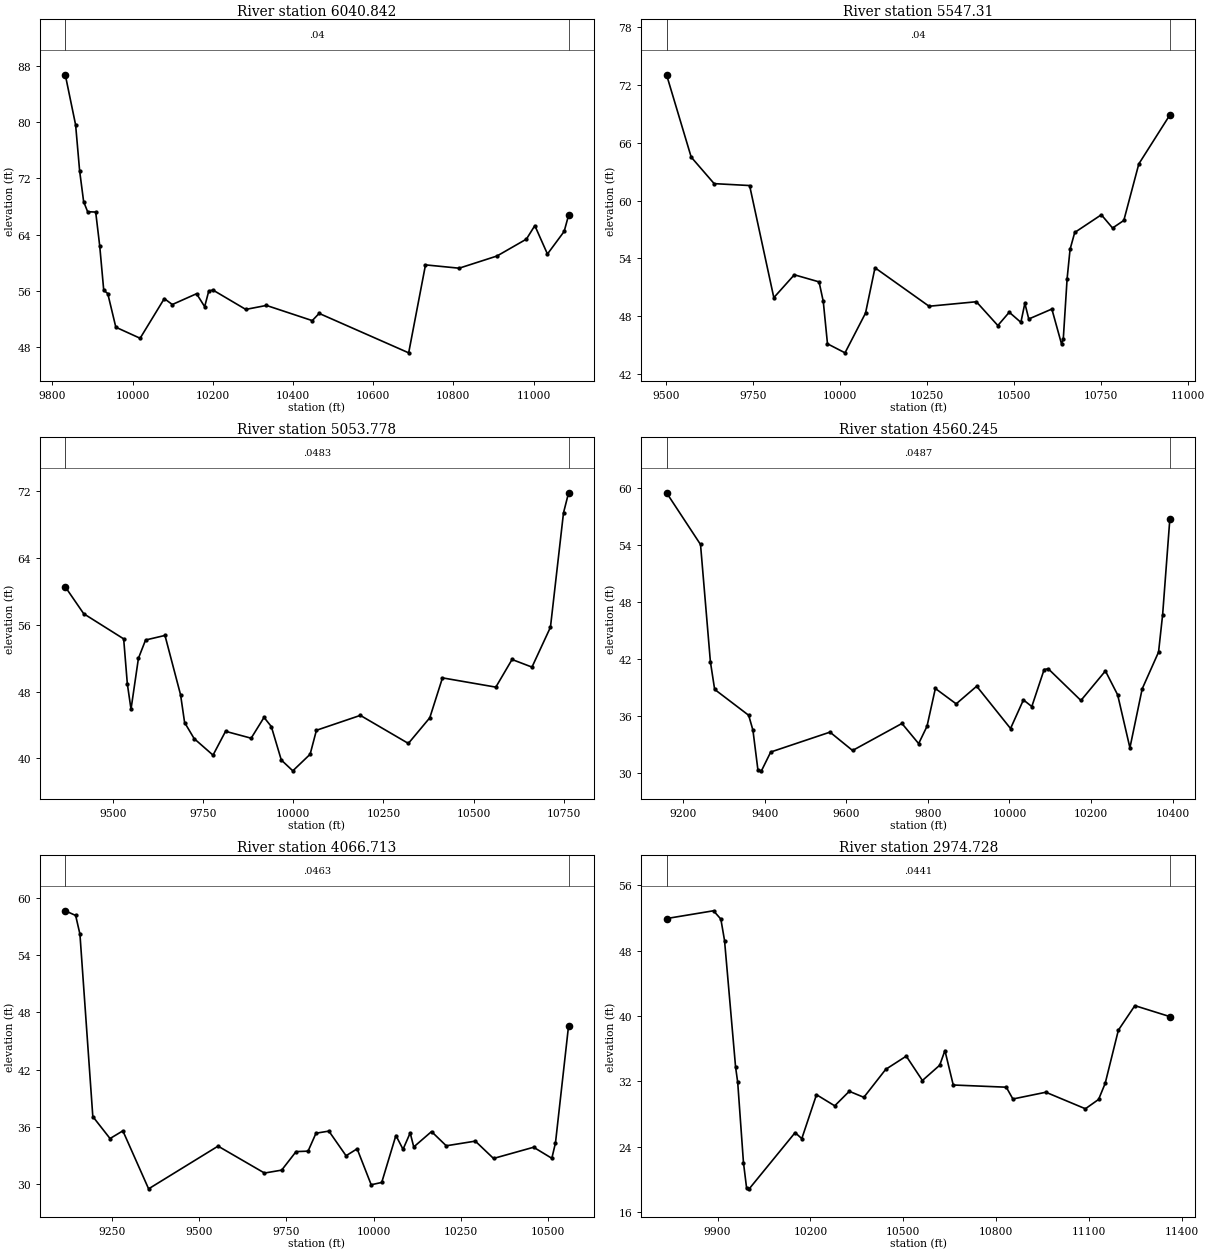
Type RM Length L Ch R = 1 ,6040.842,493.532400,493.532400,493.532400
XS GIS Cut Line= 6
818220.788127868711624.646573514 818102.79083969711618.882057558
817966.326354995711604.114038583817867.777087845711615.618340165
817634.236224323711674.342552149817004.396888275 711869.11975341
#Sta/Elev= 30
9832.25586.779679858.04679.639879868.04873.094629878.04968.696679888.05167.26073
9908.10967.21652 9918.1462.391129928.17156.069139938.20255.598749958.31750.80343
10018.8849.2272410079.1754.8787710099.1954.0383210159.6255.5755710179.8553.72792
   1019055.9495710200.2356.1092710282.3353.33947 10333.9 53.907310448.1151.74375
10465.3152.7707110688.5647.15074 10730.559.6859810814.3859.2137910908.7560.94967
10982.1563.3587411003.1265.2834111034.5861.2331411076.2764.4543511087.3266.76773
#Mann= 3 , 0 , 0
9832.255    0.04       09832.255    0.04       011087.32    0.04       0
#XS Ineff= 2 , 0
       0                               0
Bank Sta=9832.255,11087.32
Exp/Cntr=0.3,0.1

Type RM Length L Ch R = 1 , 5547.31,493.532500,493.532500,493.532500
XS GIS Cut Line= 6
 818261.43630625710971.712380347818012.772906335711089.381386596
817656.681876596711329.196274772817459.606650855711447.190052239
817189.313818385711575.437288966816991.192087493711652.004990252
#Sta/Elev= 30
9500.61973.052699571.46464.508729637.423 61.75619739.35561.558019808.95349.92321
9867.82852.296319938.97751.56013 9951.0749.529349963.16345.1344810013.5644.19615
10072.54 48.320410099.74 53.022810255.1649.0314410391.0849.4989710452.8247.03021
10485.6148.4104810519.05 47.360210530.4849.34032 10541.747.7072310608.0748.74114
10635.9645.1067110640.9545.6522110651.9151.8887410660.4154.9425610673.8256.68841
10750.2658.5235410782.5857.1488110814.9157.93542   1085863.8025310947.2768.88235
#Mann= 3 , 0 , 0
9500.619    0.04       09500.619    0.04       010947.27    0.04       0
#XS Ineff= 2 , 0
       0                               0
Bank Sta=9500.619,10947.27
Exp/Cntr=0.3,0.1

Type RM Length L Ch R = 1 ,5053.778,493.532400,493.532400,493.532400
XS GIS Cut Line= 6
818106.135490788710610.753582012817915.921941639710627.135731042
817738.151743001710696.014787001817185.016301961711060.119706397
816997.114866094711159.916639752816871.852090694711214.386725151
#Sta/Elev= 30
9368.58160.516579419.72457.303829530.37854.298879540.55748.906959550.73645.88415
9571.26651.971159591.068 54.1614 9644.8154.707619688.09447.595029699.18744.29175
9725.71742.363339777.94240.389539812.64843.240919883.55542.415499919.25144.90564
9939.48143.805669967.07539.80869    999938.5122910046.96  40.495 10064.443.36283
10186.0745.1460710319.1441.7906110378.4644.8574710413.6349.6323410561.4848.52513
10606.3751.83166 10661.650.9215410712.7855.6902410748.9569.3730110763.06 71.7725
#Mann= 3 , 0 , 0
9368.581  0.0483       09368.581  0.0483       010763.06  0.0483       0
#XS Ineff= 2 , 0
       09691.191                       0
Bank Sta=9368.581,10763.06
Exp/Cntr=0.3,0.1

Type RM Length L Ch R = 1 ,4560.245,493.532400,493.532400,493.532400
XS GIS Cut Line= 6
818088.078033196710518.660548252817700.336370338710420.570450436
  817591.3306172710423.866857098817352.528769298710467.472354647
817166.298019992710427.510111349816877.305493552 710439.78965021
#Sta/Elev= 30
9159.27459.483589242.56854.03588 9266.7841.68304 9277.2138.772959360.64736.04617
9371.07734.474799383.38330.262489391.93630.194819414.67532.176099560.01534.27166
9615.40132.337379736.436 35.18499777.38433.062889797.85834.885049818.33238.86882
9869.41637.248779919.70839.1077510002.6834.6528910034.2637.6655110054.8436.96688
10085.0840.8686710095.1540.9450410175.2337.6059510235.2940.7158110265.3238.19841
10295.3732.6208410325.4638.8320610365.5742.7017810375.5946.6458510393.3456.76933
#Mann= 3 , 0 , 0
9159.274  0.0487       09159.274  0.0487       010393.34  0.0487       0
#XS Ineff= 2 , 0
       09545.004        10221.68       0
Bank Sta=9159.274,10393.34
Exp/Cntr=0.3,0.1

Type RM Length L Ch R = 1 ,4066.713,1091.985100,1091.985100,1091.985100
XS GIS Cut Line= 6
818079.168788016710449.603928834817420.219683826709978.280916885
817393.686821401709972.255970493817304.403797448709962.476482019
817212.887461275709942.545784935816809.014476985709824.113430753
#Sta/Elev= 30
9117.09158.655849146.80558.16444  9159.156.208589195.98437.095739245.32834.79053
9282.047 35.59749355.81629.520399554.73133.995749687.773 31.17439736.95231.48149
9778.18933.422239812.56733.46931 9835.3135.348979872.194 35.57029921.37332.98713
9953.112 33.71499993.382 29.947710023.5630.1895310064.1435.1091310084.6133.66442
10105.0835.3795810115.3133.90916 10166.235.5211210208.3934.0314210291.61 34.5196
10343.8132.7045310458.6433.8788210510.8432.7205810521.2834.3392910558.8446.62963
#Mann= 3 , 0 , 0
9117.091  0.0463       09117.091  0.0463       010558.84  0.0463       0
#XS Ineff= 2 , 0
       09586.087        10231.77       0
Bank Sta=9117.091,10558.84
Exp/Cntr=0.3,0.1

Type RM Length L Ch R = 1 ,2974.728,480.322500,480.322500,480.322500
XS GIS Cut Line= 6
818209.387083501709935.064700857818280.538564861709982.737387463
817938.903923541709763.888214052817643.765034676709579.426408514
817517.385042489709524.419670478816908.788841069709302.642369896
#Sta/Elev= 30
9735.46251.951599887.06552.903179910.81751.881739922.69249.25664 9958.3233.77231
9965.22431.886679983.76322.073399993.948 18.9385 10002.318.8544210150.6125.74121
10172.0925.0005510219.5930.3828910278.4329.0194410325.4530.7985310372.4630.06071
10442.9833.48344 10509.435.10465 10561.532.1184610617.4233.9947310634.2135.78588
 10661.131.5692410832.3431.3004810853.6329.8560510960.0630.6831911087.7828.65932
11130.3629.8036311151.6431.7726211194.2238.2863711247.4341.2867711360.4839.94552
#Mann= 3 , 0 , 0
9735.462  0.0441       09735.462  0.0441       011360.48  0.0441       0
#XS Ineff= 2 , 0
       0                10853.92       0
Bank Sta=9735.462,11360.48
Exp/Cntr=0.3,0.1