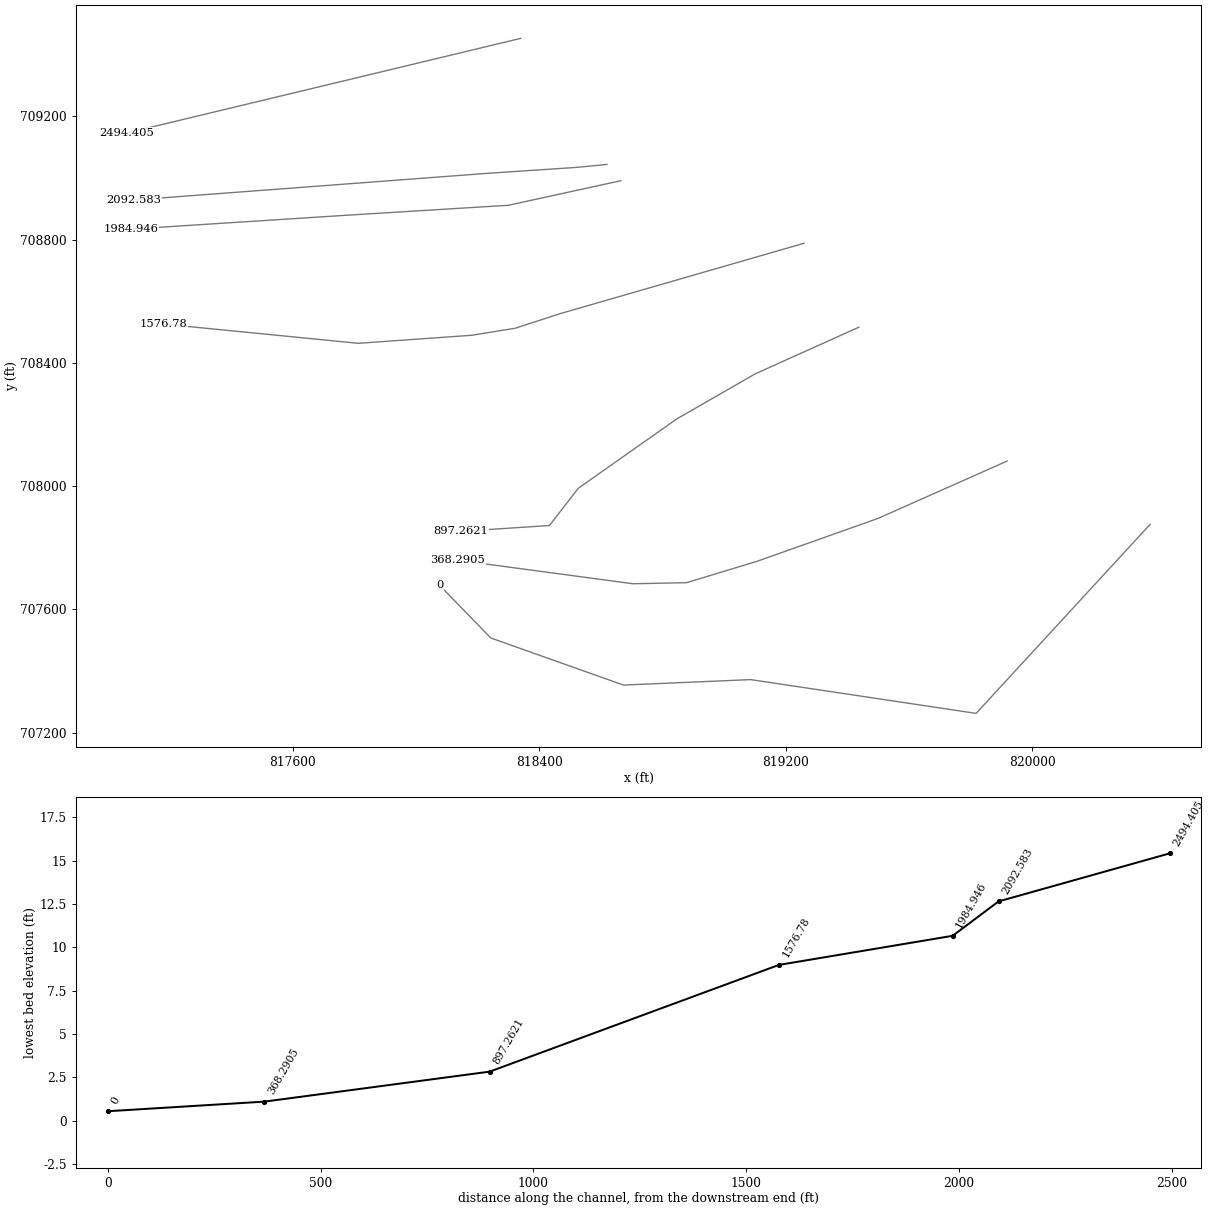
HEC-RAS study 7002_ras.prj: 7002

--- 7002_ras.g01 (geometry) --- (continued)

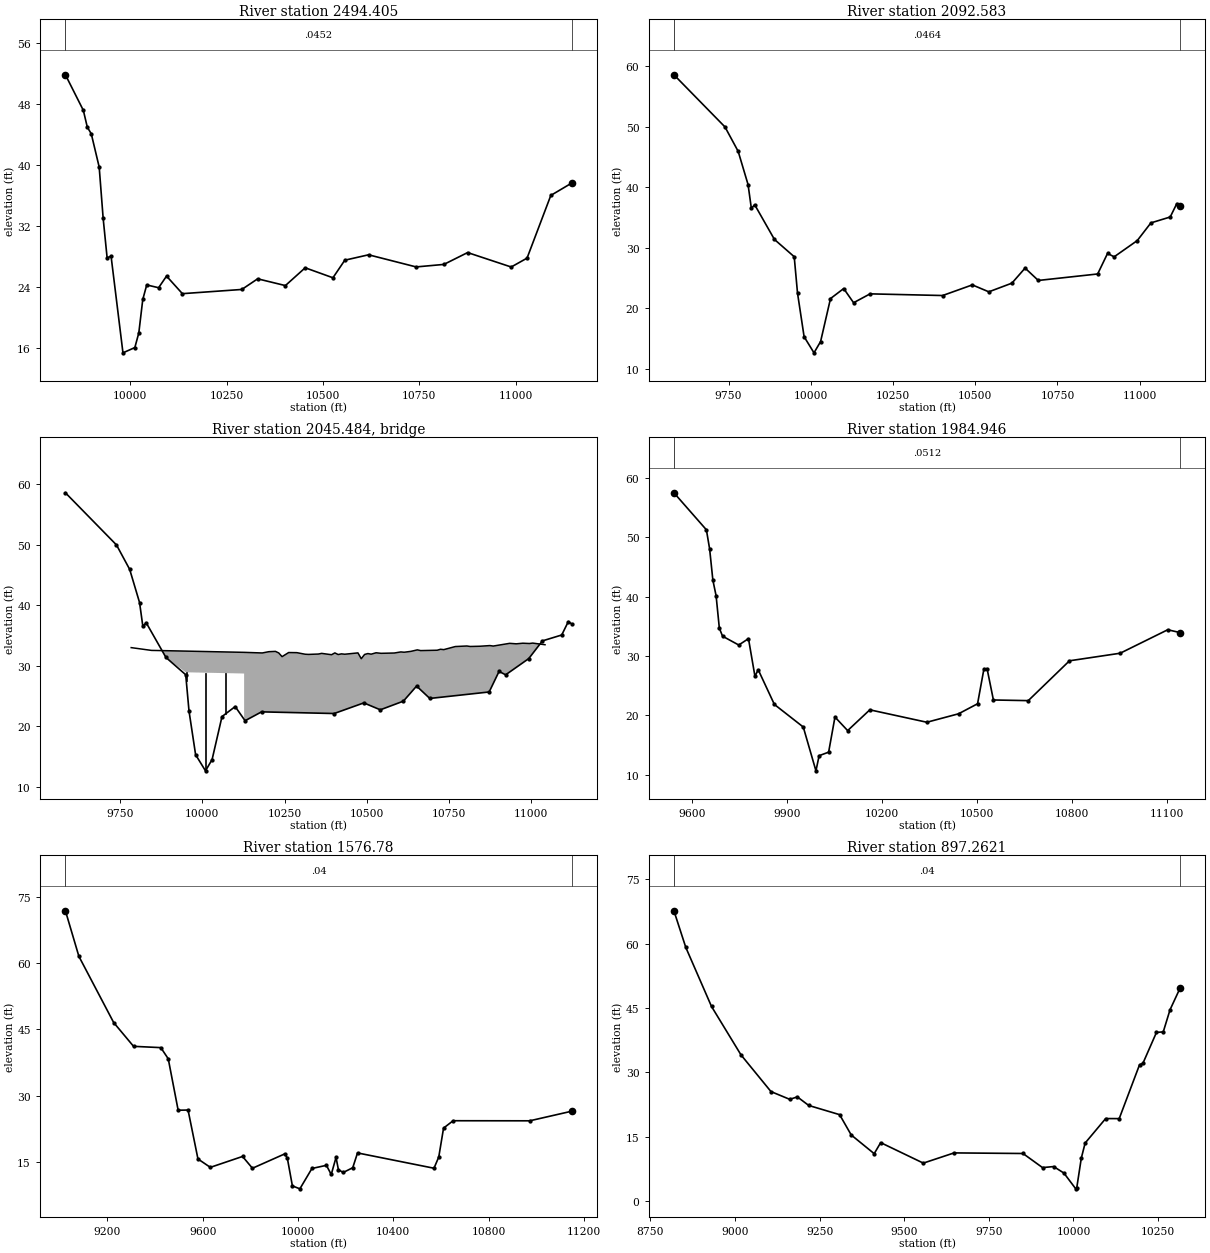
Type RM Length L Ch R = 1 ,2494.405,401.822200,401.822200,401.822200
XS GIS Cut Line= 2
818340.263623029709452.918322757817062.523931354709145.947448269
#Sta/Elev= 30
9831.47151.835069878.02247.173459888.307 44.97559898.59144.10842 9919.1639.74542
9929.44533.038839939.72927.862499950.01428.072099980.86815.4184710011.7216.10965
10022.0118.0331810032.2922.4055610042.5724.3108910073.4323.94671   1009425.46935
10135.1423.16859 10289.423.7190210330.5425.1123610402.5324.2265210453.9626.55771
10525.9525.24964 10556.827.5521310618.5128.2587510741.9226.6699710813.9226.99854
10875.6228.5504810988.7526.6596911029.8927.82189 11091.636.0358611145.5737.64584
#Mann= 3 , 0 , 0
9831.471  0.0452       09831.471  0.0452       011145.57  0.0452       0
#XS Ineff= 2 , 0
       0                10628.48       0
Bank Sta=9831.471,11145.57
Exp/Cntr=0.3,0.1

Type RM Length L Ch R = 1 ,2092.583,107.637200,107.637200,107.637200
XS GIS Cut Line= 6
818619.711909923 709043.74010118818521.043439715709034.108952981
818220.611217567709014.103522602818197.806927675709012.292458901
818195.813965208709012.124826543817085.039712995 708928.31646274
#Sta/Elev= 30
9583.877 58.59969739.18249.976759779.27145.943689809.33740.452229819.35936.50923
9829.38137.132139889.51431.387219949.647 28.53259959.669 22.53319979.71315.31329
 10009.812.6483810029.8614.5138910059.9521.6154510100.0623.2708810130.1520.92816
10180.2922.3955210400.9122.1198610491.1723.8761110541.3122.7316510611.51 24.1644
10651.6226.6543810691.7424.6100110872.25 25.681310902.3329.0757610922.3928.51568
10992.5931.1962711034.0934.1219311092.8735.0984611112.9337.3157911122.9236.94524
#Mann= 3 , 0 , 0
9583.877  0.0464       09583.877  0.0464       011122.92  0.0464       0
#XS Ineff= 2 , 0
       0                 10166.8       0
Bank Sta=9583.877,11122.92
Exp/Cntr=0.3,0.1

Type RM Length L Ch R = 3 ,2045.484,,,
BEGIN DESCRIPTION:
END DESCRIPTION:
Bridge Culvert--1,0,-1,-1, 0
Deck Dist Width WeirC Skew NumUp NumDn MinLoCord MaxHiCord MaxSubmerge Is_Ogee
39.818600,28.000000,2.6,0, 50, 50, , , 0.95, 0, 0,0,,
 9783.88 9845.68 9894.21 9894.2110127.2110127.2110182.3310202.4010222.4710232.50
10242.5410262.6110287.4810312.7810322.8110352.9210362.9510393.0610403.0910413.13
10423.1610433.1910473.3310483.3710493.4010503.4410513.4710528.3810543.5810583.71
10603.7810613.8210633.8910653.9610663.9910714.1610724.2010734.2310769.2910804.44
10814.4510844.4810874.5110884.5210934.5610954.5810974.6010994.6111004.6211042.03
   33.01   32.55   32.50   32.50   32.23   32.23   32.13   32.34   32.39   32.13
   31.52   32.20   32.18   31.92   31.89   31.95   32.06   31.84   32.14   31.87
   31.98   31.92   32.14   31.18   31.88   32.03   31.93   32.16   32.07   32.12
   32.30   32.25   32.39   32.64   32.52   32.58   32.74   32.68   33.19   33.28
   33.20   33.24   33.35   33.27   33.72   33.64   33.74   33.69   33.76   33.49
 -966.99 -967.45 -967.50   29.00   28.73 -967.77 -967.87 -967.66 -967.61 -967.87
 -968.48 -967.80 -967.82 -968.08 -968.11 -968.05 -967.94 -968.16 -967.86 -968.13
 -968.02 -968.08 -967.86 -968.82 -968.12 -967.97 -968.07 -967.84 -967.93 -967.88
 -967.70 -967.75 -967.61 -967.36 -967.48 -967.42 -967.26 -967.32 -966.81 -966.72
 -966.80 -966.76 -966.65 -966.73 -966.28 -966.36 -966.26 -966.31 -966.24 -966.51
 9783.88 9845.68 9889.10 9889.1010122.1010122.1010182.3310202.4010222.4710232.50
10242.5410262.6110287.4810312.7810322.8110352.9210362.9510393.0610403.0910413.13
10423.1610433.1910473.3310483.3710493.4010503.4410513.4710528.3810543.5810583.71
10603.7810613.8210633.8910653.9610663.9910714.1610724.2010734.2310769.2910804.44
10814.4510844.4810874.5110884.5210934.5610954.5810974.6010994.6111004.6211042.03
   33.01   32.55   32.50   32.50   32.23   32.23   32.13   32.34   32.39   32.13
   31.52   32.20   32.18   31.92   31.89   31.95   32.06   31.84   32.14   31.87
   31.98   31.92   32.14   31.18   31.88   32.03   31.93   32.16   32.07   32.12
   32.30   32.25   32.39   32.64   32.52   32.58   32.74   32.68   33.19   33.28
   33.20   33.24   33.35   33.27   33.72   33.64   33.74   33.69   33.76   33.49
 -966.99 -967.45 -967.50   29.00   28.73 -967.77 -967.87 -967.66 -967.61 -967.87
 -968.48 -967.80 -967.82 -968.08 -968.11 -968.05 -967.94 -968.16 -967.86 -968.13
 -968.02 -968.08 -967.86 -968.82 -968.12 -967.97 -968.07 -967.84 -967.93 -967.88
 -967.70 -967.75 -967.61 -967.36 -967.48 -967.42 -967.26 -967.32 -966.81 -966.72
 -966.80 -966.76 -966.65 -966.73 -966.28 -966.36 -966.26 -966.31 -966.24 -966.51
Pier Skew, UpSta & Num, DnSta & Num=  ,9951.46, 2 ,9946.35, 2 , 0 , 0 , 0 ,,
    4.00    4.00
 -967.57   32.43
    4.00    4.00
 -967.56   32.44
Pier Skew, UpSta & Num, DnSta & Num=  ,10010.71, 2 ,10005.60, 2 , 0 , 0 , 0 ,,
    4.00    4.00
 -967.64   32.36
    4.00    4.00
 -967.63   32.37
Pier Skew, UpSta & Num, DnSta & Num=  ,10069.96, 2 ,10064.85, 2 , 0 , 0 , 0 ,,
    4.00    4.00
 -967.71   32.29
    4.00    4.00
 -967.70   32.30
BR Coef=-1 , 0 , 0 ,, 0 ,,,0.8,0,1,0,
WSPro=,,,, 1 ,,,, 0 ,,,, 0 ,,,,-1 ,-1 ,-1 , 0 , 0 , 0 , 0 , 0
BC Design=,, 0 ,, 0 ,,,,,,

Type RM Length L Ch R = 1 ,1984.946,408.166100,408.166100,408.166100
XS GIS Cut Line= 4
818665.334851861708990.997307643818299.779561287708911.184714423
817750.838324077708877.282029884817075.925129629708833.879252093
#Sta/Elev= 30
9541.51257.506549644.21151.267779654.44648.043479664.68242.791929674.91840.15538
9685.15334.691949695.38933.346239746.56731.859159777.27332.935839797.74426.58504
 9807.9827.701769859.15821.851499950.52518.044989990.601 10.665710000.6213.21987
10030.68 13.813210050.7219.7308310090.79 17.444110160.9320.9450510341.2718.85087
10441.4620.2751910501.5821.9654310521.6227.8067610531.64 27.877810551.6822.60311
10661.9122.4914710792.1829.2031210952.5130.4775411102.8234.4311611141.9733.95568
#Mann= 3 , 0 , 0
9541.512  0.0512       09541.512  0.0512       011141.97  0.0512       0
#XS Ineff= 2 , 0
       0                10176.88       0
Bank Sta=9541.512,11141.97
Exp/Cntr=0.3,0.1

Type RM Length L Ch R = 1 , 1576.78,679.517600,679.517600,679.517600
XS GIS Cut Line= 6
819259.244864743  708787.8683846818470.272173911 708560.24110882
818321.996431112708512.126381606818180.091796279708489.261196539
817812.904296309708463.219529867817180.091796279708525.719529867
#Sta/Elev= 30
9023.93871.802279080.50661.50538  9226.546.552329309.92641.178919424.41840.88675
9455.60138.362719497.17826.747869538.755 26.78619580.33215.734279632.30413.83756
 9767.4316.301019809.00713.635589945.02516.891919955.58415.884489976.7049.653711
10008.098.98601410058.7313.5855810119.5114.2972810139.7612.2269510159.8616.08148
10169.8913.3207810189.9412.6797410230.04 13.755110250.0917.0986410571.0313.64044
10591.1316.1806310611.2322.7077210651.4224.3723410972.9824.3547811148.7426.51794
#Mann= 3 , 0 , 0
9023.938    0.04       09023.938    0.04       011148.74    0.04       0
#XS Ineff= 2 , 0
       0                10443.81       0
Bank Sta=9023.938,11148.74
Exp/Cntr=0.3,0.1

Type RM Length L Ch R = 1 ,897.2621,528.971600,528.971600,528.971600
XS GIS Cut Line= 6
819437.357855679708515.651304118 819100.65270519708363.977087258
818845.500592045708217.306113798818526.484519911707992.543769797
818433.034029365707871.875866681818145.261067122707853.084981263
#Sta/Elev= 30
 8819.5367.665758854.641 59.12328930.59745.356199017.79334.053279106.24325.50991
 9161.8523.693759184.09324.273979217.87122.271419309.03520.126589343.38515.38876
9411.22111.028099430.35413.604659556.3198.8263019647.22311.209169850.79711.07049
9908.465 7.78149 9941.38 8.022889971.7066.50495310006.712.82935810009.653.085695
10023.049.98012710034.39 13.511310094.99 19.215510135.0319.2021910195.0831.75655
10205.09 32.100110245.1339.3105110265.1539.4255910285.1744.5807110314.9449.65117
#Mann= 3 , 0 , 0
 8819.53    0.04       0 8819.53    0.04       010314.94    0.04       0
#XS Ineff= 2 , 0
       0                               0
Bank Sta=8819.53,10314.94
Exp/Cntr=0.3,0.1

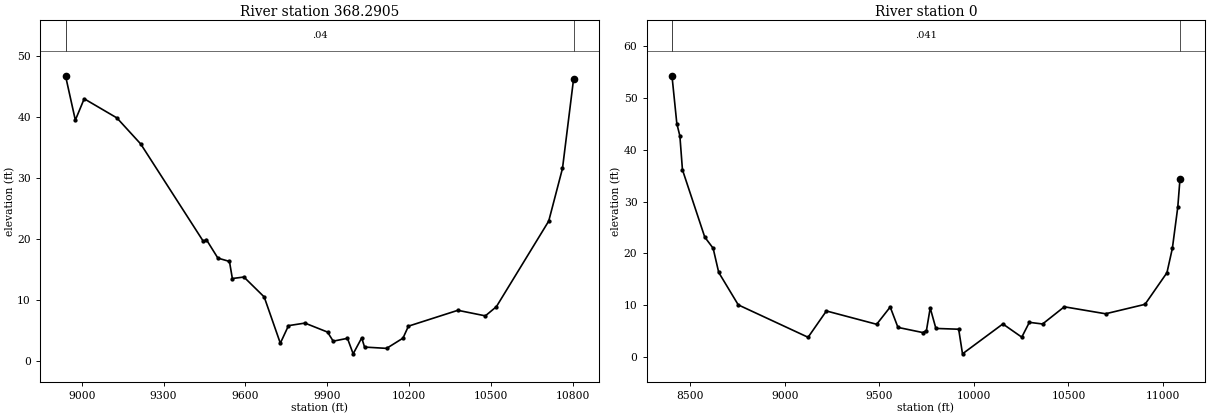
Type RM Length L Ch R = 1 ,368.2905,368.290500,368.290500,368.290500
XS GIS Cut Line= 6
819918.265260684708081.022633436819500.071437005707895.219102537
819107.066622674707755.862759039818877.899956048707686.418314591
818704.288844913707682.946092367818134.844400465707759.334981263
#Sta/Elev= 30
8940.73146.717138976.76339.441869009.25842.944879129.06739.805919216.492 35.5259
9446.22519.532089456.83519.856889499.27516.808749541.71516.257389552.32513.45796
9594.76613.700299669.03610.43635  9728.22.8418229758.1225.7253659818.3596.143836
9901.1364.6726339922.0343.181385 9974.283.6451029995.178 1.1004310026.52 3.71825
10036.972.20983310117.75 1.9975710177.773.67472910197.775.64119710378.978.242216
10479.787.33057510520.168.83325210712.0122.87691 10762.531.5172410803.0446.13793
#Mann= 3 , 0 , 0
8940.731    0.04       08940.731    0.04       010803.04    0.04       0
#XS Ineff= 2 , 0
       0                               0
Bank Sta=8940.731,10803.04
Exp/Cntr=0.3,0.1

Type RM Length L Ch R = 1 ,       0,0.000000,0.000000,0.000000
XS GIS Cut Line= 6
820382.394715488707875.747447163819817.732264727 707262.29582791
819086.199926287707371.871145755818673.415002346707354.155583128
818242.859446764707506.933360904818076.829354167707677.737759024
#Sta/Elev= 30
 8403.7354.330378429.41445.07655 8445.5242.692328459.11136.150278577.072 23.1252
8621.369 20.97138650.90116.289488754.26110.015169123.4053.7472869220.2298.837779
9485.9936.2617299557.6559.6053899598.6055.660538 9729.044.6684259749.0785.033533
9769.1169.4120629799.174 5.459859919.6665.3081869939.8770.54571510153.256.327265
10253.273.77199110293.27 6.6382310363.286.31883810478.089.64622810696.438.295129
10904.8210.1203611020.8216.2357411049.5220.9588711078.2128.9511411089.9334.44434
#Mann= 3 , 0 , 0
 8403.73   0.041       0 8403.73   0.041       011089.93   0.041       0
#XS Ineff= 2 , 0
       0                               0
Bank Sta=8403.73,11089.93
Exp/Cntr=0.3,0.1